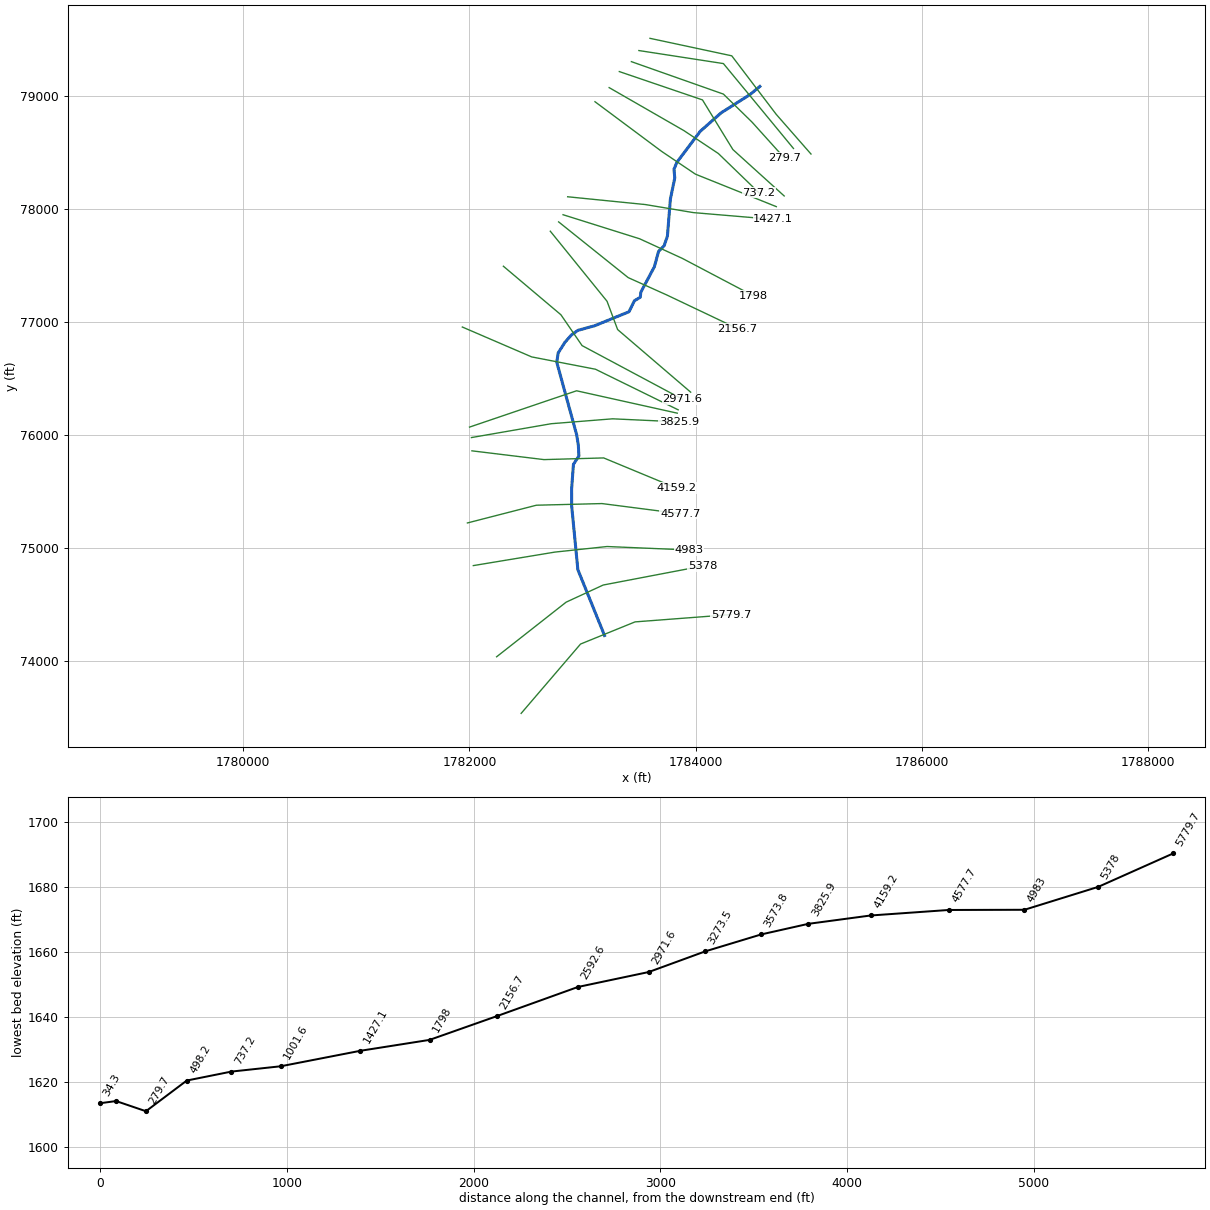
--- Beech Fork.prj (project) ---

Proj Title=Beech Fork
Current Plan=p01
Default Exp/Contr=0,0
English Units
Geom File=g01
Flow File=f01
Plan File=p01
BEGIN DESCRIPTION:
END DESCRIPTION:
DSS Export Rating Curves= 0
DSS Export Rating Curve Sorted= 0
DSS Export Volume Flow Curves= 0
DXF OffsetX= 0
DXF OffsetY= 0
DXF ScaleX= 0
DXF ScaleY= 0

--- Beech Fork.p01 (plan) ---

Plan Title=Floodplain
Program Version=4.00
Geom File=g01
Flow File=f01
K Sum by GR=0
Std Step Tol=0.01
Critical Tol=0.01
Num of Std Step Trials=20
Max Error Tol=0.3
Flow Tol Ratio=0.001
Split Flow NTrial=30
Split Flow Tol=0.02
Split Flow Ratio=0.02
Log Output Level=0
Friction Slope Method=1
Unsteady Friction Slope Method=2
Unsteady Bridges Friction Slope Method=1
Global Log Level=0
CheckData=False
Run HTab=0
Run UNet=0
Run PostProcess=0
UNET Theta=0
UNET Theta Warmup=0
UNET ZTol=0
UNET ZSATol=0
UNET MxIter=0
UNET MaxInSteps=0
UNET DtIC=0
UNET DtMin=0
UNET MaxCRTS=0
UNET WFStab=0
UNET SFStab=0
UNET WFX=0
UNET SFX=0
UNET DSS MLevel=0
UNET DZMax Abort=0
UNET Convert EG Bridges=0
UNET Use Existing IB Tables=0
UNET Froude Limit=0
UNET Froude Power=0
Write IC File=0
Echo Input=False
Echo Output=False
Write Detailed=0

--- Beech Fork.f01 (steady flow) ---

Flow Title=NFF Regression Equation
Program Version=4.00
Number of Profiles=1
Profile Names=P100yr
River Rch & RM=Beech Fork,Main      ,5779.7
2452.226
River Rch & RM=Beech Fork,Main      ,3573.8
2485.460
River Rch & RM=Beech Fork,Main      ,3273.5
3065.949
River Rch & RM=Beech Fork,Main      ,279.7
3106.737
Boundary for River Rch & Prof#=Beech Fork,Main      ,1
Up Type=0
Dn Type=3
Dn Slope=0.009128

--- Beech Fork.g01 (geometry) ---

Geom Title=USGS 10m DEM
Program Version=4.00

River Reach=Beech Fork      ,Main
Reach XY= 30
     1783194.329       74222.077     1782958.358       74805.726
     1782903.911       75368.486     1782903.131       75519.169
     1782919.229       75738.416     1782967.525       75812.776
     1782962.925       75905.534      1782948.36       75998.293
     1782772.042       76643.002     1782784.308       76725.028
     1782843.336       76818.553     1782902.364       76885.247
     1782958.326        76925.11     1783107.812       76966.507
     1783410.619       77089.929     1783458.148       77187.287
     1783510.369       77219.002     1783514.876        77263.18
     1783634.836        77488.63     1783672.029       77625.014
     1783721.091       77674.843     1783750.003       77759.499
     1783776.286       78087.273     1783814.992       78274.884
     1783808.483        78354.05     1783834.547       78414.611
     1784040.762       78689.053     1784226.279       78853.105
     1784479.613       79013.653     1784567.298       79086.051

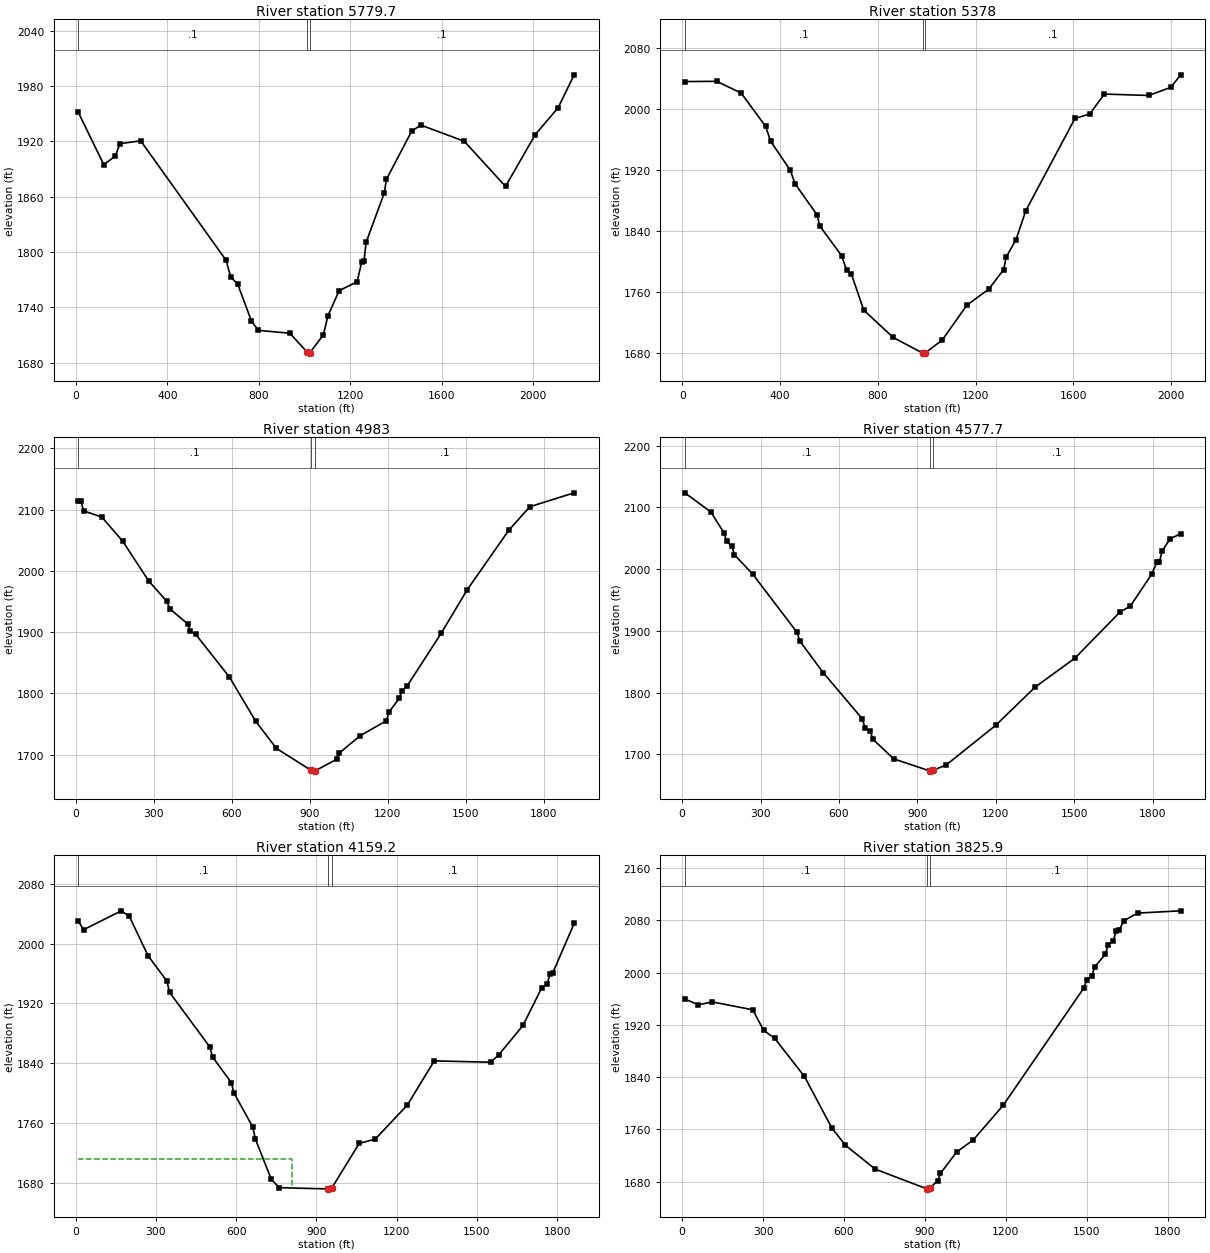
Type RM Length L Ch R = 1 ,5779.7  ,400.8,401.7,402.6
XS GIS Cut Line= 5
     1782457.141       73532.275     1782982.042       74146.388
     1783190.555       74231.337     1783463.828       74342.671
     1784312.382        74407.53
#Sta/Elev= 30
    10.1 1951.38   121.2 1894.76   171.7 1903.89   191.9  1917.4   282.8 1920.56
   656.4 1790.97   676.6 1772.95   706.9  1765.3   767.5 1725.04   797.8 1714.96
   935.1 1711.91 1009.16 1691.94  1013.4 1690.31  1023.2 1690.79  1082.2 1710.24
  1101.9 1730.82  1151.1 1758.09  1229.7 1767.64  1249.4 1788.94  1259.3 1789.81
  1269.1 1810.45  1348.1  1863.8  1358.1 1878.85  1468.3 1930.98  1508.3 1937.58
  1698.6 1920.01  1878.8 1871.07  2008.9 1927.27  2109.1 1956.48  2179.1 1992.08
#Mann= 3 , 0 , 0
    10.1      .1       0 1009.16    .045       0  1023.2      .1       0
Bank Sta=1009.16,1023.2
XS Rating Curve= 0 ,0
Exp/Cntr=0.3,0.1

Type RM Length L Ch R = 1 ,5378    ,401.5,394.9,388.3
XS GIS Cut Line= 4
     1782240.198       74033.489     1782854.668       74517.438
      1783182.78       74669.358     1784061.775       74837.676
#Sta/Elev= 30
      10  2036.2   140.4 2036.49   240.7 2021.09   340.9 1977.31     361 1957.98
   441.2  1920.1   461.3 1902.11   551.5  1861.2   561.6 1847.14   651.8 1807.69
   671.9  1788.8   691.9 1783.39   742.1 1736.42   862.5 1700.58   983.3 1680.02
  993.11    1680   993.3 1680.07  1063.4 1697.17  1163.9 1742.83  1254.4 1764.12
  1314.7 1789.56  1324.7 1805.89    1365 1828.75  1405.2 1866.81  1606.3 1987.77
  1666.6 1993.64    1727 2019.82    1908 2017.94  1998.5 2028.61  2038.7 2045.03
#Mann= 3 , 0 , 0
      10      .1       0   983.3    .045       0   993.3      .1       0
Bank Sta=983.3,993.3
XS Rating Curve= 0 ,0
Exp/Cntr=0.3,0.1

Type RM Length L Ch R = 1 ,4983    ,407,405.3,403.7
XS GIS Cut Line= 4
     1782034.476       74841.416     1782756.374       74961.109
     1783216.383       75010.372     1783938.341       74979.811
#Sta/Elev= 30
      10 2114.13      20 2113.68    30.1  2097.8   100.2 2087.72   180.4 2048.41
   280.7 1983.34   350.8 1949.99   360.9 1938.33     431 1913.13   441.1 1900.94
   461.1 1896.37   591.4 1826.42   691.7  1754.6     772    1710  905.89 1674.03
   912.8 1672.95   919.7 1673.24  1003.3 1692.22  1013.4  1702.4  1093.8  1730.7
  1194.4 1755.08  1204.4 1769.14  1244.6 1791.79  1254.6 1804.16  1274.7 1812.05
  1405.2 1897.73  1505.5 1968.94  1666.1 2066.46  1746.4 2104.56    1917 2127.27
#Mann= 3 , 0 , 0
      10      .1       0  905.89    .045       0   919.7      .1       0
Bank Sta=905.89,919.7
XS Rating Curve= 0 ,0
Exp/Cntr=0.3,0.1

Type RM Length L Ch R = 1 ,4577.7  ,418.1,418.5,418.8
XS GIS Cut Line= 4
      1781982.11       75219.197     1782591.796       75376.294
     1783171.571       75390.871     1783863.533       75301.486
#Sta/Elev= 30
      10 2123.45   109.9 2092.39   159.9 2058.59   169.9 2044.67   189.9 2037.43
   199.9  2023.1   269.8 1991.91   439.7 1897.39   449.7 1883.71   539.7 1832.25
   689.6 1757.42   699.6 1742.49   719.6  1737.2   729.6 1724.61   809.6 1692.74
   946.7  1673.3  949.84 1672.89   959.6 1674.19  1009.6 1682.69  1199.6 1746.98
  1351.1 1809.14  1502.8 1855.75  1674.7 1930.18  1715.1  1940.2    1796 1991.37
  1816.3 2010.79  1826.4 2011.79  1836.5 2029.29  1866.8 2048.82  1907.3 2057.29
#Mann= 3 , 0 , 0
      10      .1       0   946.7    .045       0   959.6      .1       0
Bank Sta=946.7,959.6
XS Rating Curve= 0 ,0
Exp/Cntr=0.3,0.1

Type RM Length L Ch R = 1 ,4159.2  ,332.9,333.3,333.8
XS GIS Cut Line= 4
     1782021.752       75858.007     1782659.123       75780.258
      1783186.52       75795.219     1783827.455       75528.907
#Sta/Elev= 30
      10 2030.12    30.1 2018.85   170.6  2044.1   200.7 2036.66   270.9  1983.8
   341.1 1949.99   351.1 1934.83   501.6 1861.72   511.7 1848.32   581.9 1814.02
   591.9 1799.98     662 1754.45     672 1738.27   731.7 1684.18   761.6 1673.16
   944.5 1671.46   950.7 1671.19   956.9 1672.26  1060.2  1732.5  1119.9 1738.15
  1240.1 1783.85  1340.7 1843.05  1551.9 1841.21  1582.1 1851.22  1672.6 1890.62
  1743.1 1941.32  1763.2  1945.7  1773.2 1959.55  1783.3  1960.5  1863.8 2027.18
#Mann= 3 , 0 , 0
      10      .1       0   944.5    .045       0   956.9      .1       0
#XS Ineff= 2 , 0
          807.68 1711.32
Permanent Ineff=
       F       F
Bank Sta=944.5,956.9
XS Rating Curve= 0 ,0
Exp/Cntr=0.3,0.1

Type RM Length L Ch R = 1 ,3825.9  ,247.2,252.1,257.1
XS GIS Cut Line= 4
     1782017.793       75975.591      1782722.71       76098.192
     1783265.349       76141.662     1783852.016       76114.586
#Sta/Elev= 30
    10.1 1959.58    60.5 1950.54   110.9 1955.14     262 1943.01   302.3 1911.45
   342.6 1899.61   453.5 1840.99   554.3  1762.6   604.6 1735.98   715.5 1699.26
     907 1669.01   917.1 1668.62  919.71 1670.78   947.4 1681.72   957.4 1692.81
  1017.9 1725.62  1078.4  1743.7  1189.3 1796.63  1488.8 1976.55  1498.8 1988.55
  1518.7 1995.39  1528.6 2008.51  1568.5 2028.15  1578.4 2042.93  1598.3 2048.41
  1608.3 2064.32  1618.2 2064.52  1638.1 2079.57  1687.9 2091.01  1847.2 2094.46
#Mann= 3 , 0 , 0
    10.1      .1       0     907    .045       0  919.71      .1       0
Bank Sta=907,919.71
XS Rating Curve= 0 ,0
Exp/Cntr=0.3,0.1

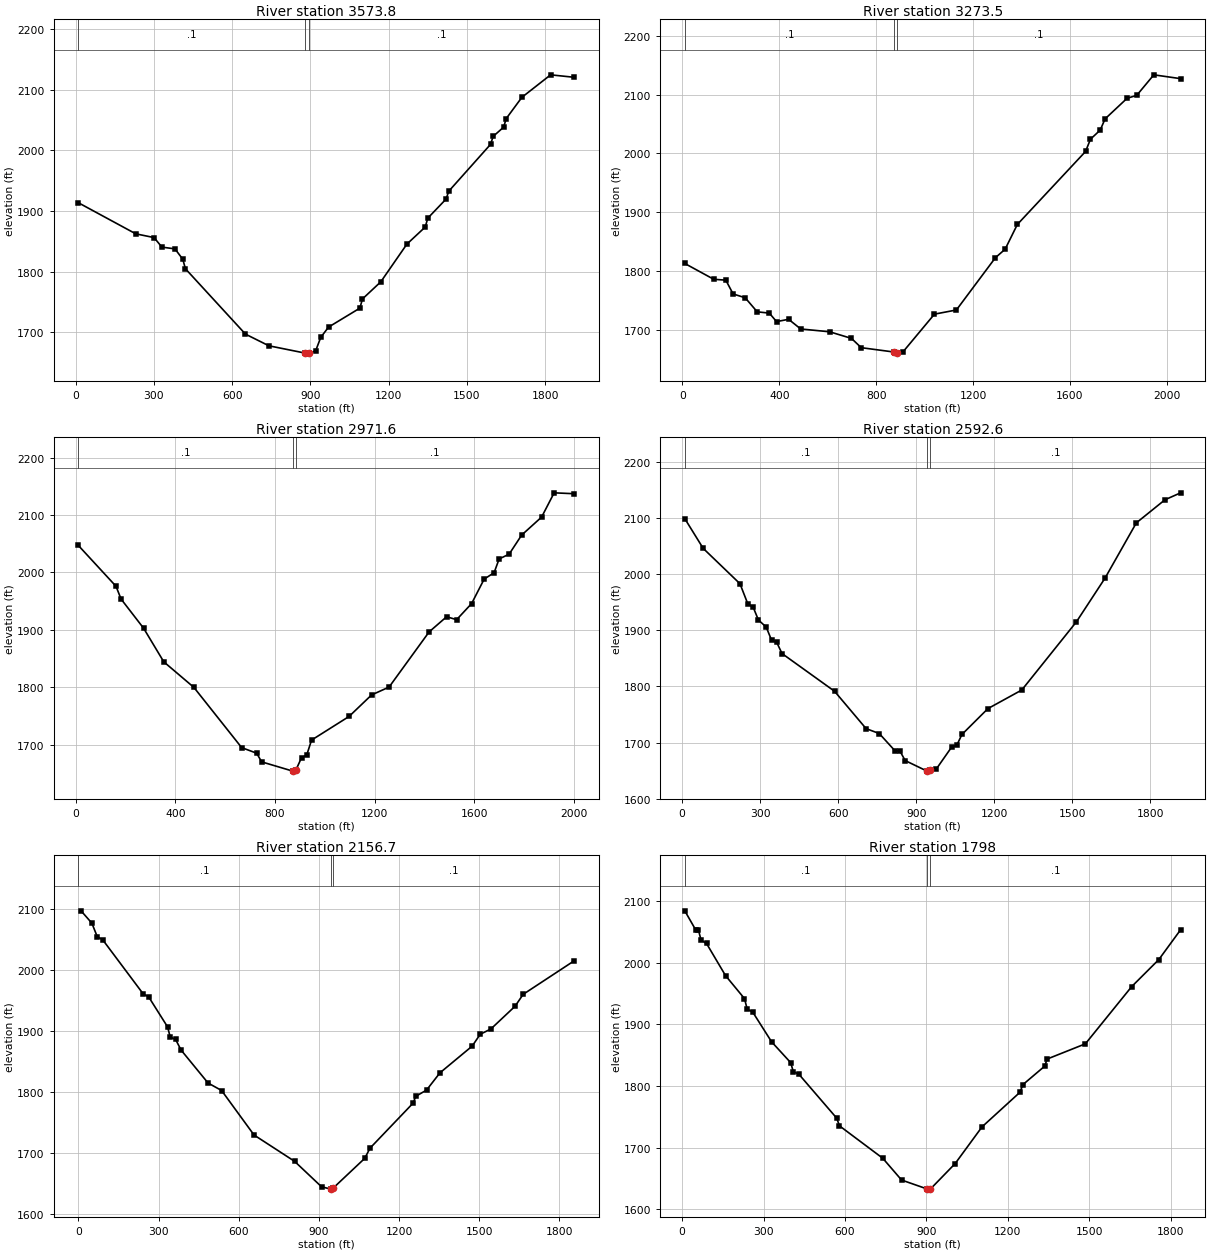
Type RM Length L Ch R = 1 ,3573.8  ,310.8,300.3,289.7
XS GIS Cut Line= 4
     1782000.812       76068.269     1782692.787       76303.914
     1782947.134       76389.943      1783837.35       76191.702
#Sta/Elev= 30
      10 1913.72   230.3 1862.35   300.4 1856.17   330.5 1840.41   380.5 1837.53
   410.6 1820.41   420.6 1804.72   650.9 1696.75   740.9 1677.45   880.2 1665.37
   890.1 1665.36   893.9 1665.63   919.9 1668.91   939.8 1691.48   969.7 1708.37
  1089.7 1739.66  1099.7 1754.87  1169.9 1783.08  1270.1 1845.41  1340.3 1873.56
  1350.3 1888.29  1420.4 1919.83  1430.5 1932.69  1590.8 2010.06  1600.8 2023.25
  1640.9 2038.43  1650.9 2052.63  1711.1 2087.78  1821.3 2124.91  1911.5 2120.85
#Mann= 3 , 0 , 0
      10      .1       0   880.2    .045       0   893.9      .1       0
Bank Sta=880.2,893.9
XS Rating Curve= 0 ,0
Exp/Cntr=0.3,0.1

Type RM Length L Ch R = 1 ,3273.5  ,317.6,301.9,286.3
XS GIS Cut Line= 4
     1781937.225       76954.744     1782550.448       76689.997
     1783114.042       76580.914     1783845.266       76221.216
#Sta/Elev= 30
      10 1812.72   129.6 1785.81   179.4 1784.34   209.4 1760.84   259.2  1754.4
     309 1730.41   358.9 1728.25   388.8 1713.77   438.6 1717.71   488.5 1701.25
   608.1 1696.44   698.1 1685.18   738.4 1669.41  872.46 1662.06   879.4 1660.13
  886.43  1660.4   909.6 1661.68  1040.6 1726.48  1131.2 1733.57  1292.3 1822.58
  1332.5 1837.06  1382.8 1879.14  1664.5 2003.43  1684.7 2024.28  1724.9 2039.75
    1745 2058.83  1835.6 2093.82  1875.8 2098.96  1946.2 2133.84  2056.9 2127.33
#Mann= 3 , 0 , 0
      10      .1       0  872.46    .045       0  886.43      .1       0
Bank Sta=872.46,886.43
XS Rating Curve= 0 ,0
Exp/Cntr=0.3,0.1

Type RM Length L Ch R = 1 ,2971.6  ,383.8,378.9,374
XS GIS Cut Line= 4
     1782300.044       77493.363     1782808.739       77063.216
      1782995.76       76790.167      1783881.39       76316.029
#Sta/Elev= 30
    10.1 2046.97   161.5 1975.76   181.7  1953.6   272.5 1902.59   353.3 1844.22
   474.4 1799.61   666.2 1694.73   726.4 1685.02   746.4 1669.93   870.5 1653.91
   876.8 1653.78  883.77 1655.51   906.9 1677.41   926.9  1681.2     947 1707.88
  1097.6 1749.05    1188 1786.52  1258.3 1800.22  1419.1 1896.33  1489.4 1922.73
  1529.6 1917.65  1589.8 1945.69  1640.1 1988.27  1680.2 1999.52  1700.3 2023.44
  1740.5 2031.75  1790.7 2064.94  1871.1 2096.46  1921.3 2138.62  2001.7 2137.06
#Mann= 3 , 0 , 0
    10.1      .1       0   870.5    .045       0  883.77      .1       0
Bank Sta=870.5,883.77
XS Rating Curve= 0 ,0
Exp/Cntr=0.3,0.1

Type RM Length L Ch R = 1 ,2592.6  ,418.5,435.9,453.3
XS GIS Cut Line= 4
     1782714.798       77803.631     1783216.443       77182.909
     1783309.953       76932.302     1783955.553        76377.82
#Sta/Elev= 30
    10.1 2099.09    80.8 2046.12   222.3 1983.08   252.6 1946.97   272.8 1941.56
     293 1918.66   323.3 1905.71   343.5 1882.71   363.7 1878.52   383.9 1858.71
   585.9 1791.51   707.2 1724.91   757.7 1716.21   817.9  1685.6   837.7 1684.62
   857.5 1667.99  940.14 1649.51   946.7 1649.18  953.65  1651.1   976.4 1652.45
  1035.9 1691.85  1055.7    1695  1075.6 1714.47  1175.7 1760.61  1305.9 1793.75
  1516.1 1915.36  1626.2 1993.29  1746.4 2091.62  1856.5 2132.75  1916.6 2145.09
#Mann= 3 , 0 , 0
    10.1      .1       0  940.14    .045       0  953.65      .1       0
Bank Sta=940.14,953.65
XS Rating Curve= 0 ,0
Exp/Cntr=0.3,0.1

Type RM Length L Ch R = 1 ,2156.7  ,358.9,358.7,358.4
XS GIS Cut Line= 4
     1782788.211       77886.257     1783403.464       77392.372
      1783743.84       77239.015     1784369.622       76940.979
#Sta/Elev= 30
    10.1 2096.72    50.6 2076.53    70.8 2054.28      91 2049.34   242.8 1960.39
     263 1955.67   333.8 1906.41   343.9 1889.72   364.1 1885.65   384.4 1868.34
   485.5 1814.21   536.1 1801.96   657.5 1728.94   809.1 1685.81     910 1644.06
   944.2 1640.26   950.4 1640.16   954.2 1642.09  1071.5 1690.55  1091.7 1707.46
  1252.7 1781.25  1262.7 1792.44  1302.9 1802.58  1353.2 1830.95  1473.7 1874.75
  1503.8 1894.14    1544 1902.98  1634.4 1940.24  1664.6 1959.73  1855.4 2014.69
#Mann= 3 , 0 , 0
       0      .1       0   944.2    .045       0   954.2      .1       0
Bank Sta=944.2,954.2
XS Rating Curve= 0 ,0
Exp/Cntr=0.3,0.1

Type RM Length L Ch R = 1 ,1798    ,365.8,370.9,376.1
XS GIS Cut Line= 4
     1782827.441       77949.692     1783504.454       77736.489
     1783881.501       77563.038     1784511.156       77230.848
#Sta/Elev= 30
      10 2084.05      50 2053.24      60 2053.24      70 2036.51      90 2031.14
     160 1979.06   229.9 1941.76   239.9  1924.6   259.9 1920.14   329.9 1871.63
   399.9 1838.03   409.9 1823.22   429.9 1819.34   569.8 1747.85   579.8 1735.49
   739.4 1682.92   808.6 1647.65  902.37 1633.21   907.4 1632.88   914.9 1633.03
  1006.2 1674.39  1105.1 1733.83  1245.1 1790.02  1255.2 1802.13  1335.4 1832.03
  1345.4 1843.85  1485.8 1868.45  1656.2  1961.1  1756.5 2005.11  1836.7 2053.39
#Mann= 3 , 0 , 0
      10      .1       0  902.37    .045       0   914.9      .1       0
Bank Sta=902.37,914.9
XS Rating Curve= 0 ,0
Exp/Cntr=0.3,0.1

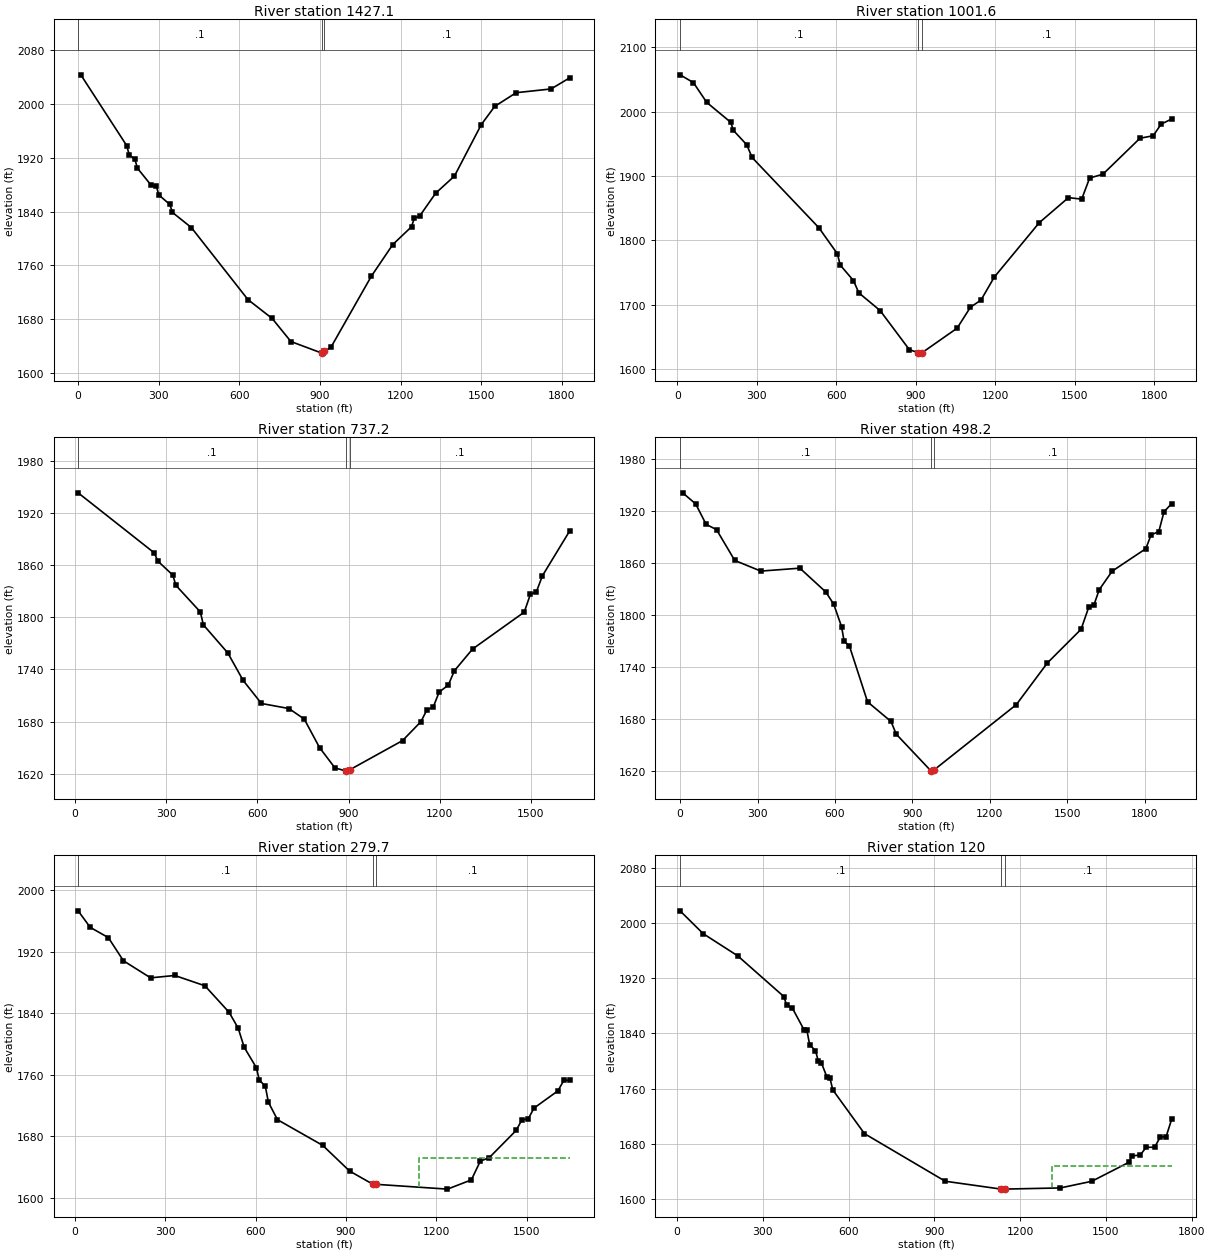
Type RM Length L Ch R = 1 ,1427.1  ,434.2,425.5,416.8
XS GIS Cut Line= 4
     1782868.266       78108.675      1783556.82       78039.462
     1783979.486       77968.394     1784685.737        77908.64
#Sta/Elev= 30
      10 2043.34   180.5  1938.2   190.6 1923.73   210.6 1918.59   220.6  1904.5
   270.8 1879.64   290.9 1877.43   300.9 1864.51     341 1850.62     351 1838.72
   421.2 1816.24   631.8 1709.14   721.9 1681.06   791.7 1646.75   906.3 1629.62
   911.3 1629.52   916.3 1632.01   941.2 1638.61  1090.7 1743.73  1170.5  1790.9
  1240.4 1817.45  1250.4 1829.89  1270.4 1833.21  1330.3 1867.36  1400.1  1892.8
    1500 1969.38  1549.9 1996.38  1629.7 2016.77  1759.5 2022.33  1829.4 2038.97
#Mann= 3 , 0 , 0
       0      .1       0   906.3    .045       0   916.3      .1       0
Bank Sta=906.3,916.3
XS Rating Curve= 0 ,0
Exp/Cntr=0.3,0.1

Type RM Length L Ch R = 1 ,1001.6  ,264.3,264.4,264.5
XS GIS Cut Line= 4
     1783109.744       78950.684     1783698.955       78510.752
     1783998.188       78308.771      1784712.79       78021.216
#Sta/Elev= 30
    10.1 2057.17    60.4 2045.13   110.8 2014.34   201.5 1983.39   211.5 1970.79
   261.9 1948.47     282 1928.73   533.9 1819.72   604.4 1778.93   614.5 1761.72
   664.8 1737.46     685  1718.4   765.4 1690.91   875.7 1630.21  909.74 1625.35
   915.8 1624.76  922.43 1625.02  1056.2 1663.53  1106.4 1696.07  1146.4 1707.26
  1196.4 1742.85  1366.5  1827.5  1476.5 1866.37  1526.5 1864.02  1556.5 1896.82
  1606.5 1902.69  1746.6 1958.63  1796.6 1962.54  1826.6 1980.66  1866.6 1988.58
#Mann= 3 , 0 , 0
    10.1      .1       0  909.74    .045       0  922.43      .1       0
Bank Sta=909.74,922.43
XS Rating Curve= 0 ,0
Exp/Cntr=0.3,0.1

Type RM Length L Ch R = 1 ,737.2   ,247.7,239,230.3
XS GIS Cut Line= 4
     1783235.145       79075.553     1783897.197       78694.032
     1784200.169        78492.05     1784559.248       78144.193
#Sta/Elev= 30
    10.1 1942.86   261.4 1873.68   271.5 1864.73   321.7 1848.33   331.8 1836.57
   412.2 1806.04   422.3 1791.16   502.7 1758.89     553 1727.38   613.3 1700.84
   703.8 1695.02   754.1 1682.96   804.6 1650.16   855.1 1626.89   890.7  1623.3
   895.6 1623.12  903.66 1624.59  1077.7 1658.21  1138.2 1679.95  1158.2  1693.8
  1178.2 1696.31  1198.2 1713.98  1228.2 1721.94  1248.2 1738.39  1308.2 1763.41
  1478.2  1805.8  1498.2 1826.08  1518.2 1829.26  1538.2  1847.7  1628.2 1899.34
#Mann= 3 , 0 , 0
    10.1      .1       0   890.7    .045       0  903.66      .1       0
Bank Sta=890.7,903.66
XS Rating Curve= 0 ,0
Exp/Cntr=0.3,0.1

Type RM Length L Ch R = 1 ,498.2   ,213.5,218.5,223.6
XS GIS Cut Line= 4
     1783324.915       79217.689     1784059.927       78966.813
     1784328.817       78526.954     1784782.431       78115.776
#Sta/Elev= 30
    10.1 1940.54    60.5  1927.8   100.9 1904.28   141.2 1898.19   211.8 1862.76
   312.7  1850.5     464 1853.86   564.8 1826.38   595.1 1812.39   625.4 1786.67
   635.4 1769.83   655.6 1764.61   726.2 1700.06   817.1 1677.46   837.3 1662.85
     972 1620.55   978.8 1620.36     982 1621.32  1302.2 1696.81  1422.7 1744.85
  1553.1 1783.55  1583.2 1809.29  1603.3 1811.86  1623.4 1829.07  1673.6 1850.43
  1804.1 1876.31  1824.1 1892.12  1854.2 1895.96  1874.3 1918.73  1904.4 1928.25
#Mann= 3 , 0 , 0
       0      .1       0     972    .045       0     982      .1       0
Bank Sta=972,982
XS Rating Curve= 0 ,0
Exp/Cntr=0.3,0.1

Type RM Length L Ch R = 1 ,279.7   ,161.9,159.7,157.5
XS GIS Cut Line= 4
     1783431.532       79305.688     1784245.096       79018.113
      1784498.26       78769.865     1784783.376       78452.796
#Sta/Elev= 30
      10 1973.31    50.2 1951.79   110.4 1938.44   160.5 1908.28   250.8 1886.03
   331.1 1889.12   431.4 1875.68   511.7 1841.14   541.8 1820.57   561.9 1795.58
     602 1769.24   612.1 1753.01   632.1 1744.76   642.2 1724.17   672.3 1701.36
   822.8 1667.86   912.1 1634.44   988.7 1617.45   998.7 1617.21  1237.3 1610.91
  1316.6 1622.91  1346.4 1647.34  1376.1 1651.89  1465.4 1687.28  1485.2 1701.55
    1505 1701.96  1524.9 1716.47  1604.2 1738.85    1624 1752.52  1643.9 1752.58
#Mann= 3 , 0 , 0
      10      .1       0   988.7    .045       0   998.7      .1       0
#XS Ineff= 2 , 0
                         1143.35         1651.71
Permanent Ineff=
       F       F
Bank Sta=988.7,998.7
XS Rating Curve= 0 ,0
Exp/Cntr=0.3,0.1

Type RM Length L Ch R = 1 ,120     ,86.5,85.7,84.9
XS GIS Cut Line= 4
     1783497.895       79404.003     1784245.096       79288.482
      1784591.66       78868.181     1784864.487       78536.365
#Sta/Elev= 30
    10.1  2018.1    90.7 1985.02   211.7 1952.78     373 1893.69   383.1 1881.19
   403.2 1876.68   443.6 1845.57   453.6 1845.24   463.7 1823.28   483.9 1815.27
     494  1799.5   504.1 1797.85   524.2 1776.51   534.3  1775.6   544.4 1758.12
   655.3  1694.6   937.7 1625.51 1133.34 1614.07  1139.4 1614.04 1145.76 1614.09
  1340.8 1615.78  1450.7 1625.44  1580.6 1653.02  1590.6 1662.16  1620.5 1663.63
  1640.5 1674.63  1670.5 1674.99  1690.5 1689.88  1710.4  1689.9  1730.4 1716.04
#Mann= 3 , 0 , 0
    10.1      .1       0 1133.34    .045       0 1145.76      .1       0
#XS Ineff= 2 , 0
                         1312.44         1646.93
Permanent Ineff=
       F       F
Bank Sta=1133.34,1145.76
XS Rating Curve= 0 ,0
Exp/Cntr=0.3,0.1

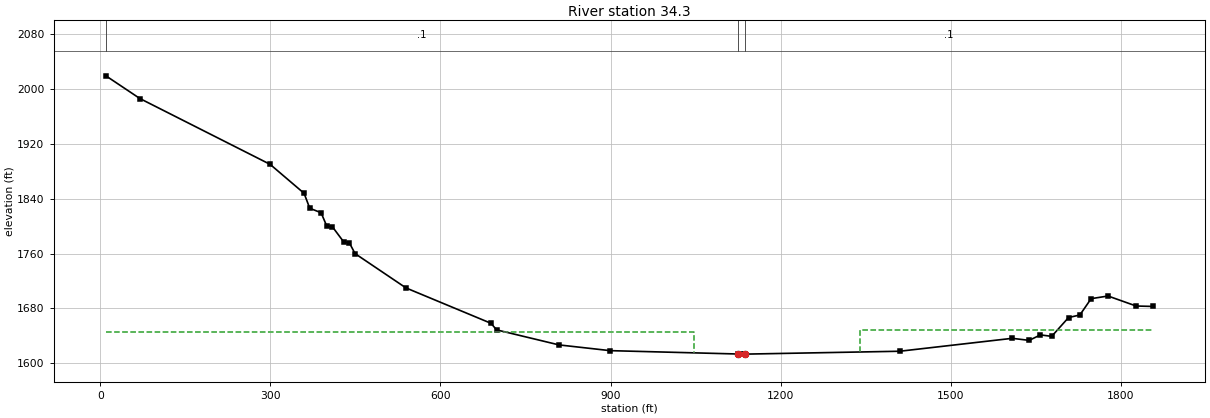
Type RM Length L Ch R = 1 ,34.3    ,31.5,34.3,37
XS GIS Cut Line= 4
     1783596.211       79512.151     1784318.833       79357.303
     1784712.097       78838.686     1785019.335       78487.207
#Sta/Elev= 30
      10 2019.22    69.9 1986.13   299.6 1890.12   359.5 1847.91   369.5 1826.11
   389.5 1819.55   399.5 1800.12   409.5 1799.03   429.4 1776.99   439.4  1775.6
   449.4 1759.98   539.3 1709.88   689.1 1658.34   699.1 1648.73   809.1 1626.82
   899.2 1618.46  1125.5 1613.54 1129.52 1613.38 1137.24 1613.39  1409.8 1617.58
  1608.4 1636.42  1638.2 1633.44  1658.1 1641.44  1677.9 1639.29  1707.7 1666.74
  1727.6 1670.44  1747.5 1694.26  1777.3 1698.13  1826.9 1683.54  1856.7 1682.92
#Mann= 3 , 0 , 0
      10      .1       0  1125.5    .045       0 1137.24      .1       0
#XS Ineff= 2 , 0
         1047.89 1646.19 1340.42         1648.58
Permanent Ineff=
       F       F
Bank Sta=1125.5,1137.24
XS Rating Curve= 0 ,0
Exp/Cntr=0.3,0.1

Chan Stop Cuts=-1
Use User Specified Reach Order=0